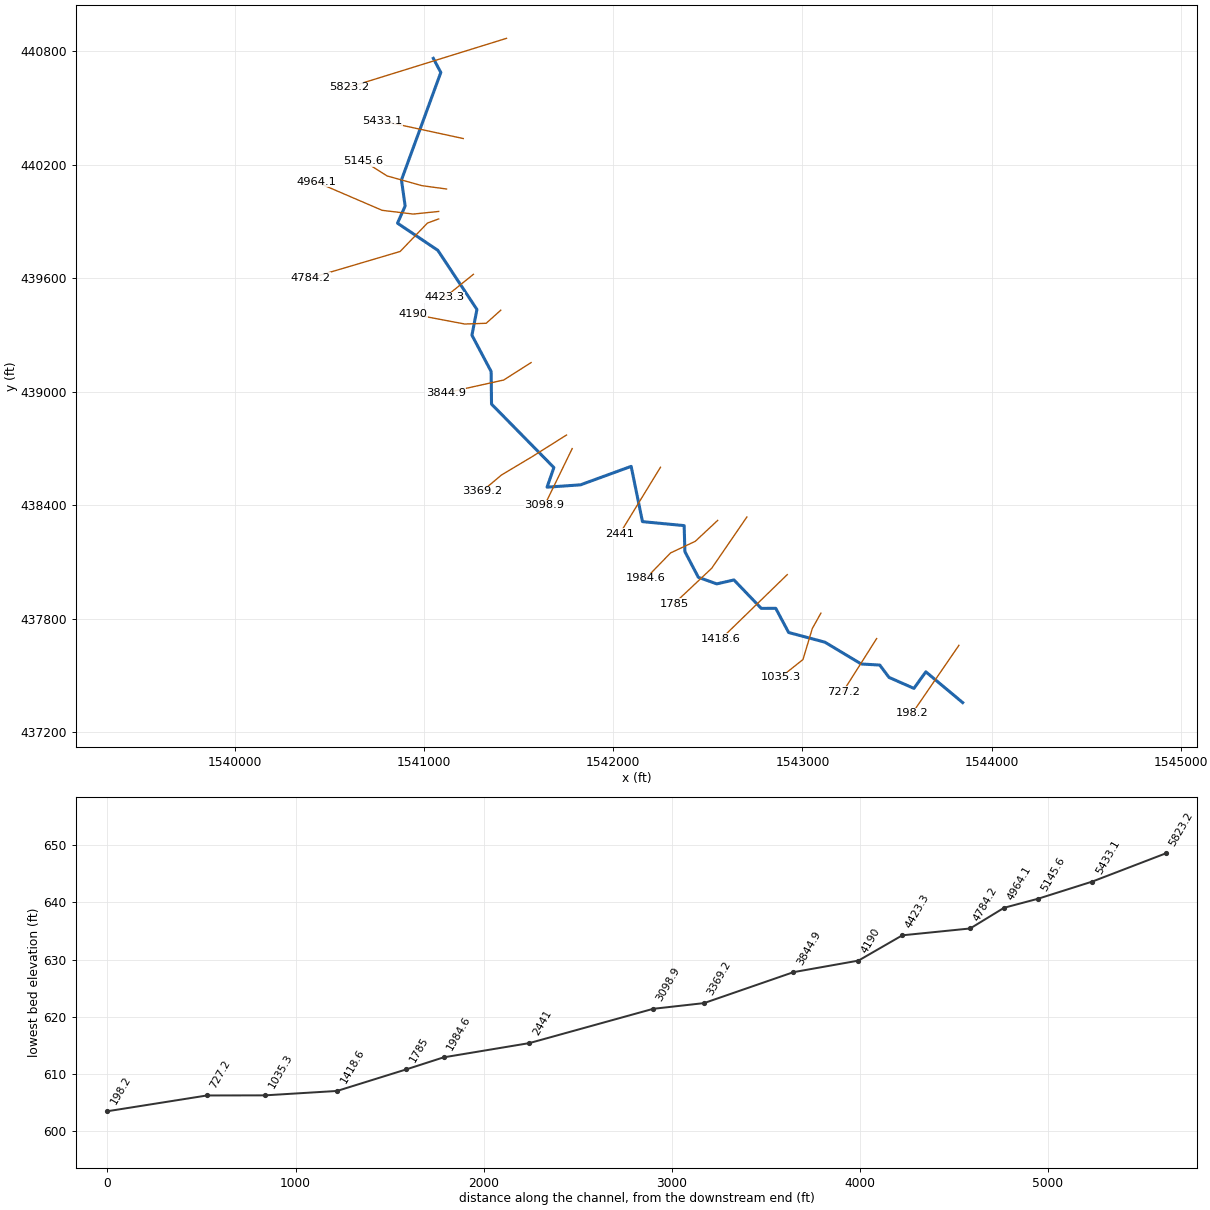
--- PATRICKCR.prj (project) ---

Proj Title=PATRICKCR
Current Plan=p01
Default Exp/Contr=0,0
English Units
Geom File=g01
Flow File=f01
Plan File=p01
BEGIN DESCRIPTION:
END DESCRIPTION:
DSS Export Rating Curves= 0
DSS Export Rating Curve Sorted= 0
DSS Export Volume Flow Curves= 0
DXF OffsetX= 0
DXF OffsetY= 0
DXF ScaleX= 0
DXF ScaleY= 0

--- PATRICKCR.p01 (plan) ---

Plan Title=Floodplain
Program Version=4.00
Geom File=g01
Flow File=f01
K Sum by GR=0
Std Step Tol=0.01
Critical Tol=0.01
Num of Std Step Trials=20
Max Error Tol=0.3
Flow Tol Ratio=0.001
Split Flow NTrial=30
Split Flow Tol=0.02
Split Flow Ratio=0.02
Log Output Level=0
Friction Slope Method=1
Unsteady Friction Slope Method=2
Unsteady Bridges Friction Slope Method=1
Global Log Level=0
CheckData=False
Run HTab=0
Run UNet=0
Run PostProcess=0
UNET Theta=0
UNET Theta Warmup=0
UNET ZTol=0
UNET ZSATol=0
UNET MxIter=0
UNET MaxInSteps=0
UNET DtIC=0
UNET DtMin=0
UNET MaxCRTS=0
UNET WFStab=0
UNET SFStab=0
UNET WFX=0
UNET SFX=0
UNET DSS MLevel=0
UNET DZMax Abort=0
UNET Convert EG Bridges=0
UNET Use Existing IB Tables=0
UNET Froude Limit=0
UNET Froude Power=0
Write IC File=0
Echo Input=False
Echo Output=False
Write Detailed=0

--- PATRICKCR.f01 (steady flow) ---

Flow Title=NFF Regression Equation
Program Version=4.00
Number of Profiles=1
Profile Names=P100yr
River Rch & RM=PATRICKCR,Main      ,5823.2
378.7352
River Rch & RM=PATRICKCR,Main      ,4964.1
383.9423
River Rch & RM=PATRICKCR,Main      ,4784.2
517.0813
River Rch & RM=PATRICKCR,Main      ,4190
535.7979
River Rch & RM=PATRICKCR,Main      ,1785
588.4542
River Rch & RM=PATRICKCR,Main      ,198.2
641.7824
Boundary for River Rch & Prof#=PATRICKCR,Main      ,1
Up Type=0
Dn Type=3
Dn Slope=0.002361

--- PATRICKCR.g01 (geometry) ---

Geom Title=Geometry
Program Version=4.00

River Reach=PATRICKCR       ,Main
Reach XY= 30
     1541049.814      440761.487     1541089.471      440686.855
     1540881.622      440119.166     1540901.038      439981.181
     1540860.655      439890.616      1541073.81       439747.14
     1541280.305      439434.655     1541253.842      439298.749
     1541355.319      439107.065      1541357.42       438934.68
     1541686.811      438599.592     1541650.843       438495.83
     1541827.481       438508.14     1542095.152       438605.75
     1542154.943      438313.694     1542375.185      438292.708
      1542379.01       438155.34      1542450.17      438019.519
     1542547.187      437984.938     1542638.245      438005.583
     1542782.417      437855.469     1542859.127      437855.648
     1542927.193      437727.998     1543118.915      437676.826
     1543310.436      437561.675     1543408.686      437555.955
     1543457.564      437490.765     1543589.143      437432.741
     1543652.021      437520.264     1543846.691      437357.629

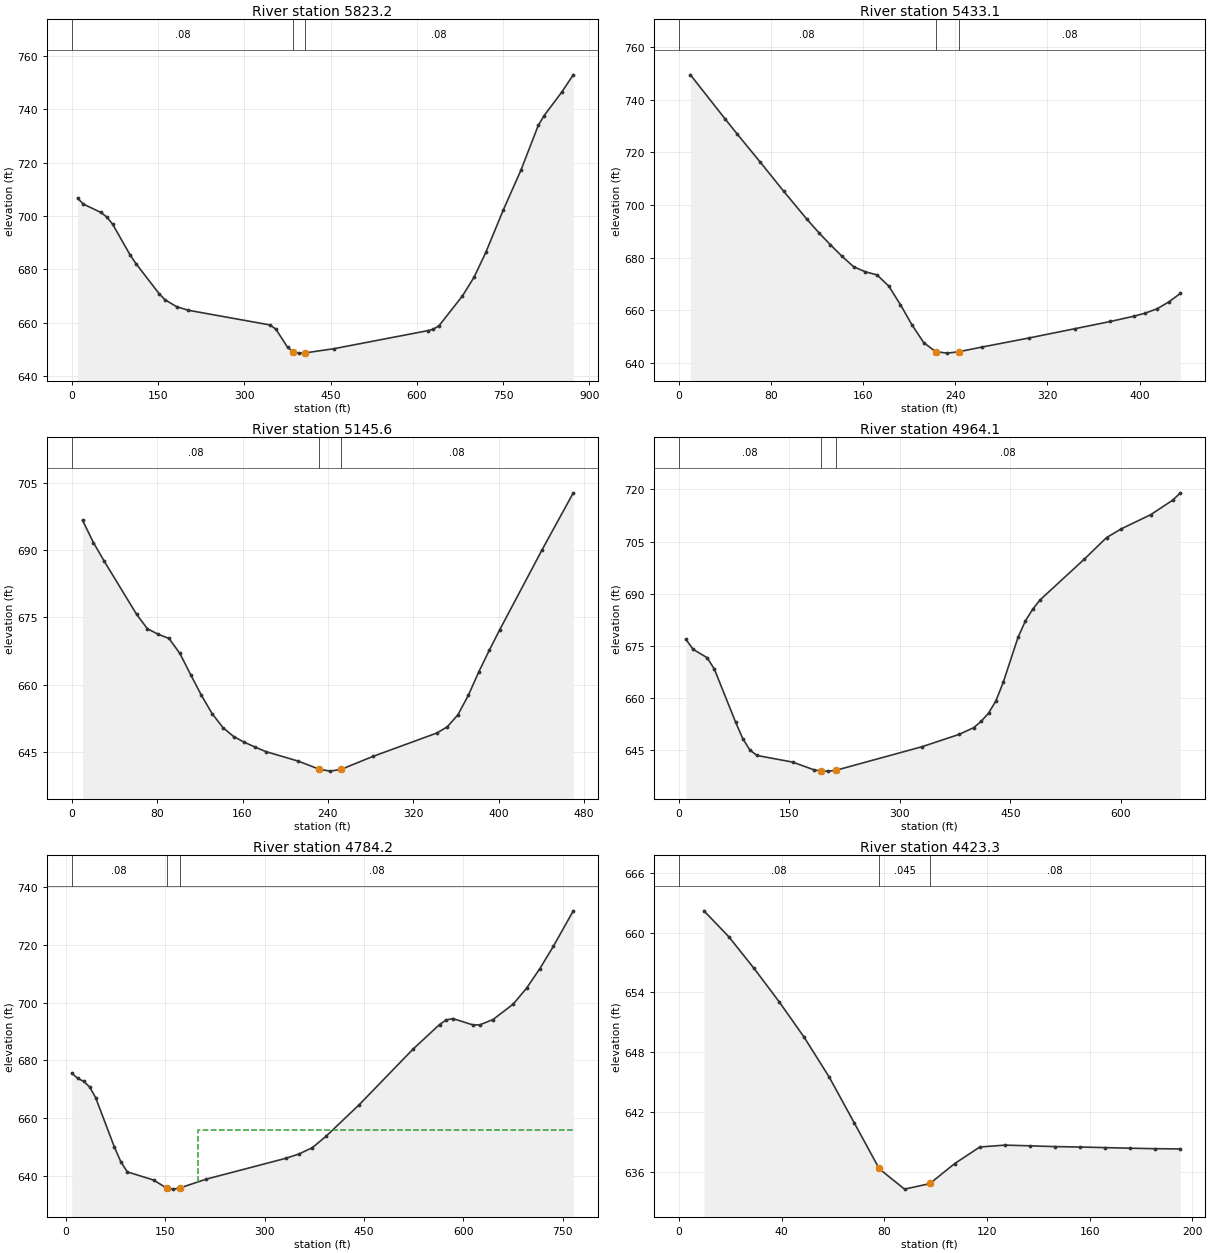
Type RM Length L Ch R = 1 ,5823.2  ,403,390,378.3
XS GIS Cut Line= 2
     1541436.437      440867.183     1540603.401      440608.652
#Sta/Elev= 30
    10.1  706.65    20.3  704.44    50.7   701.3    60.9  699.59      71  696.94
   101.4  685.42   111.6  682.16   152.1  670.82   162.3  668.55   182.6  665.98
   202.8  664.65   344.8  659.15     355  657.57   375.3   650.8   385.5  648.99
   395.5  648.59   405.5  648.66   456.4  650.27   618.7  656.99   628.8  657.54
     639  658.93   679.5  670.04   699.8   677.1   720.1  686.35   750.5  702.25
     781  717.07   811.4  733.95   821.5   737.6   851.9  746.32   872.2  752.87
#Mann= 3 , 0 , 0
       0     .08       0   385.5    .045       0   405.5     .08       0
Bank Sta=385.5,405.5
XS Rating Curve= 0 ,0
Exp/Cntr=0.3,0.1

Type RM Length L Ch R = 1 ,5433.1  ,289.2,287.6,286
XS GIS Cut Line= 2
      1541207.94      440337.818     1540782.344      440429.708
#Sta/Elev= 28
    10.1   749.5    40.5  732.57    50.6  727.05    70.9   716.2    91.1  705.21
   111.4  694.48   121.5  689.51   131.6  684.88   141.8  680.46   151.9  676.47
     162  674.59   172.1  673.41   182.3  669.14   192.4   662.1   202.5  654.35
   212.6  647.67   222.9  644.24   232.9  643.66   242.9  644.17   263.3  645.98
   303.8   649.4   344.3  652.99   374.6  655.69   394.9  657.68     405  658.88
   415.2  660.53   425.3  663.11   435.4  666.36
#Mann= 3 , 0 , 0
       0     .08       0   222.9    .045       0   242.9     .08       0
Bank Sta=222.9,242.9
XS Rating Curve= 0 ,0
Exp/Cntr=0.3,0.1

Type RM Length L Ch R = 1 ,5145.6  ,174,181.4,188.8
XS GIS Cut Line= 4
     1541119.714      440071.114     1540989.295      440088.898
     1540805.523      440140.276     1540681.032      440219.317
#Sta/Elev= 30
    10.1  696.74    20.3  691.74    30.4   687.6    60.8  675.69    70.9  672.48
      81  671.25    91.1  670.32   101.3  666.97   111.4  662.22   121.5   657.6
   131.6  653.49   141.7  650.38   151.7  648.39   161.8   647.1   171.8  646.04
   181.8  645.03     212  642.91   232.1  641.07   242.1  640.66   252.1  641.03
   282.3  643.96   342.1  649.18   351.9  650.58   361.8  653.25   371.6  657.62
   381.4  662.86   391.3  667.73   401.1  672.31   440.4  690.01   469.9  702.86
#Mann= 3 , 0 , 0
       0     .08       0   232.1    .045       0   252.1     .08       0
Bank Sta=232.1,252.1
XS Rating Curve= 0 ,0
Exp/Cntr=0.3,0.1

Type RM Length L Ch R = 1 ,4964.1  ,160.4,180,199.5
XS GIS Cut Line= 4
     1541078.217      439952.551     1540943.846      439938.719
     1540779.834      439958.479     1540430.074      440108.659
#Sta/Elev= 30
     9.6  676.94    19.3  674.08    38.6  671.63    48.2   668.4    77.2   653.1
    86.8  648.44    96.5  645.13   106.1  643.57   154.5  641.67   183.7  639.43
   193.1  639.09   203.1  639.07   213.1   639.3   330.3  646.09   380.4  649.61
   400.4  651.56   410.5  653.38   420.5  655.71   430.5  659.25   440.5   664.6
   460.5  677.46   470.6  682.23   480.6  685.62   490.6  688.28   550.7  699.98
   580.7  706.14   600.8  708.66   640.9  712.75   670.9  716.95   680.9     719
#Mann= 3 , 0 , 0
       0     .08       0   193.1    .045       0   213.1     .08       0
Bank Sta=193.1,213.1
XS Rating Curve= 0 ,0
Exp/Cntr=0.3,0.1

Type RM Length L Ch R = 1 ,4784.2  ,364,360.8,357.7
XS GIS Cut Line= 4
     1541078.217      439913.031     1541018.935      439891.294
     1540874.684      439741.115     1540400.434      439600.816
#Sta/Elev= 30
       9  675.62      18  673.78    27.1  672.75    36.1  670.79    45.1  667.08
    73.1  650.17      83  644.94    92.9  641.42   132.6  638.58   152.3   635.8
   162.3  635.45   172.3  635.86   211.9   638.9   331.9  646.11   352.1  647.63
   372.3  649.83   392.5  653.69     443   664.7   523.7  683.82   564.1  692.42
   574.2     694   584.3  694.47   614.5  692.27   624.6  692.29   644.8  694.14
   675.1  699.45   695.3  704.97   715.5  711.78   735.7  719.43   765.9  731.76
#Mann= 3 , 0 , 0
       9     .08       0   152.3    .045       0   172.3     .08       0
#XS Ineff= 2 , 0
                             200          655.87
Permanent Ineff=
       F       F
Bank Sta=152.3,172.3
XS Rating Curve= 0 ,0
Exp/Cntr=0.3,0.1

Type RM Length L Ch R = 1 ,4423.3  ,249.4,233.3,217.2
XS GIS Cut Line= 2
     1541261.989      439620.576     1541109.833      439498.061
#Sta/Elev= 22
     9.8   662.2    19.5  659.59    29.3  656.42    39.1  653.06    48.8  649.51
    58.6  645.49    68.4  640.87    77.9  636.37    78.1  636.28    87.9  634.25
    97.7   634.8    97.9  634.84   107.4  636.81   117.2  638.48     127  638.67
   136.7   638.6   146.5  638.52   156.3  638.48     166  638.42   175.8  638.36
   185.6  638.31   195.3  638.29
#Mann= 3 , 0 , 0
       0     .08       0    77.9    .045       0    97.9     .08       0
Bank Sta=77.9,97.9
XS Rating Curve= 0 ,0
Exp/Cntr=0.3,0.1

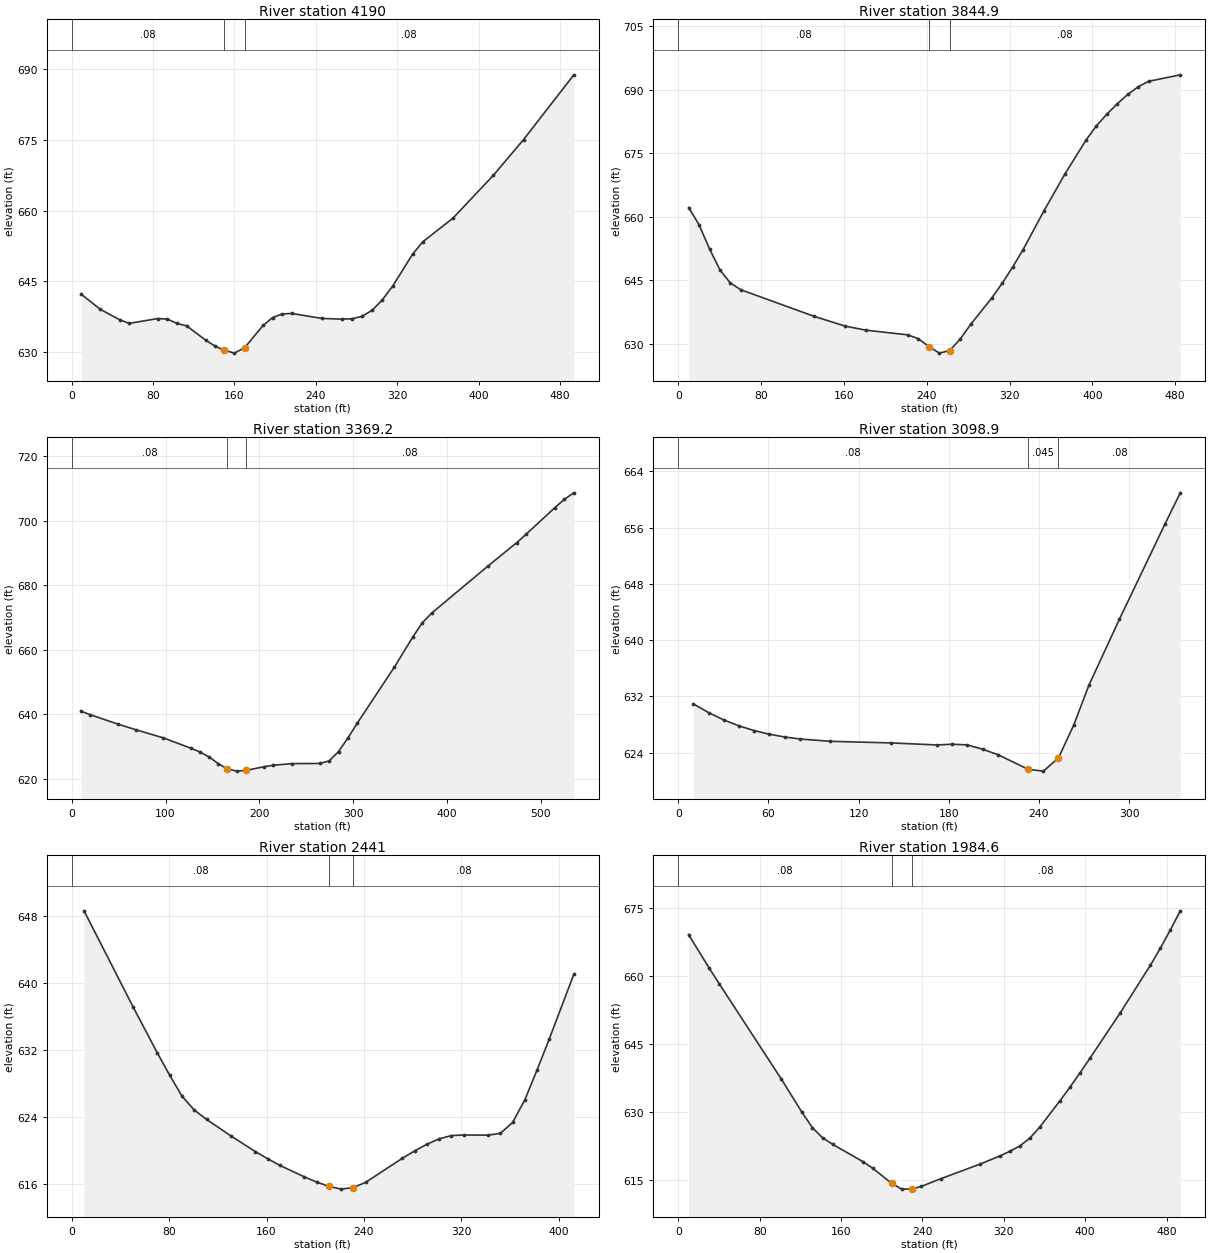
Type RM Length L Ch R = 1 ,4190    ,340.2,345.2,350.1
XS GIS Cut Line= 4
      1541406.24      439430.876     1541329.174      439361.714
      1541216.54      439357.762     1540943.846      439409.139
#Sta/Elev= 30
     9.4  642.27    28.2  639.07    47.1  636.88    56.5  636.12    84.7  637.14
    94.1  637.02   103.5   636.1   112.9   635.6   131.7  632.56   141.1  631.28
   149.9  630.43   159.9  629.82   169.9  630.95   188.1  635.68   197.5  637.35
   206.9  638.11   216.3  638.22     246  637.16   265.8  637.01   275.7   637.1
   285.6  637.62   295.5  638.91   305.4   641.1   315.4  643.96   335.2  650.78
   345.1  653.37   374.8  658.38   414.5  667.44   444.2     675   493.7  688.72
#Mann= 3 , 0 , 0
       0     .08       0   149.9    .045       0   169.9     .08       0
Bank Sta=149.9,169.9
XS Rating Curve= 0 ,0
Exp/Cntr=0.3,0.1

Type RM Length L Ch R = 1 ,3844.9  ,467.3,475.6,484
XS GIS Cut Line= 3
     1541566.424      439153.941     1541421.948      439062.018
     1541115.761       438994.17
#Sta/Elev= 30
    10.1   662.2    20.1  658.12    30.2  652.43    40.3  647.46    50.4  644.34
    60.4  642.78   130.9  636.52   161.2  634.18   181.4  633.22   221.8  632.11
   231.9  631.21   242.2  629.34   252.2   627.8   262.2  628.41   272.4  631.15
   282.5  634.61   302.8  640.82   312.9  644.31     323  648.13   333.1  652.27
   353.3  661.45   373.6  670.17   393.8  678.11   403.9  681.51     414  684.25
   424.2  686.75   434.3  688.93   444.4  690.75   454.5  692.02   484.9  693.54
#Mann= 3 , 0 , 0
       0     .08       0   242.2    .045       0   262.2     .08       0
Bank Sta=242.2,262.2
XS Rating Curve= 0 ,0
Exp/Cntr=0.3,0.1

Type RM Length L Ch R = 1 ,3369.2  ,257.3,270.4,284
XS GIS Cut Line= 4
     1541753.571      438771.405     1541571.775      438656.794
      1541409.74      438559.968     1541308.961      438474.999
#Sta/Elev= 30
     9.8  640.93    19.5  639.88    48.8  636.99    68.4   635.2    97.7  632.68
     127  629.48   136.8   628.3   146.5  626.77   156.3  624.69   165.8  623.09
   175.8  622.38   185.8   622.6   205.1  623.75   214.9  624.19   234.8  624.71
   264.6  624.75   274.5  625.55   284.5  628.43   294.4  632.61   304.3  637.14
   344.1  654.62   363.9  664.01   373.9  668.33   383.8  671.32   444.2  685.99
   474.6  693.17   484.8  695.82   515.2     704   525.3  706.58   535.5   708.6
#Mann= 3 , 0 , 0
       0     .08       0   165.8    .045       0   185.8     .08       0
Bank Sta=165.8,185.8
XS Rating Curve= 0 ,0
Exp/Cntr=0.3,0.1

Type RM Length L Ch R = 1 ,3098.9  ,657.9,657.9,660.1
XS GIS Cut Line= 2
     1541783.664       438699.74     1541637.437      438399.381
#Sta/Elev= 23
    10.1  630.94    20.2   629.7    30.4  628.65    40.5  627.81    50.6  627.14
    60.7  626.63    70.9  626.23      81  625.95   101.2  625.62   141.7  625.39
   172.1   625.1   182.2  625.21   192.3  625.11   202.5   624.5   212.6  623.73
     233  621.63     243  621.38     253  623.25   263.2  627.94   273.3  633.61
   293.6  642.99   323.9  656.52   334.1  660.95
#Mann= 3 , 0 , 0
       0     .08       0     233    .045       0     253     .08       0
Bank Sta=233,253
XS Rating Curve= 0 ,0
Exp/Cntr=0.3,0.1

Type RM Length L Ch R = 1 ,2441    ,471.5,456.4,437
XS GIS Cut Line= 2
     1542250.011      438600.938     1542034.622      438249.202
#Sta/Elev= 30
    10.1  648.59    50.3  637.14    70.4   631.6    80.5  628.95    90.5  626.48
   100.6  624.82   110.7   623.7   130.8  621.72   150.9  619.85     161     619
     171  618.21   191.1  616.84   201.2  616.22   211.3  615.71   221.3  615.38
   231.3  615.57   241.4  616.19   271.6  619.07   281.7  619.94   291.7  620.74
   301.8  621.38   311.8  621.77   321.9  621.84     342  621.82   352.1  622.04
   362.1  623.34   372.2  626.05   382.3  629.64   392.3  633.33   412.4  641.03
#Mann= 3 , 0 , 0
       0     .08       0   211.3    .045       0   231.3     .08       0
Bank Sta=211.3,231.3
XS Rating Curve= 0 ,0
Exp/Cntr=0.3,0.1

Type RM Length L Ch R = 1 ,1984.6  ,197.1,199.5,206.1
XS GIS Cut Line= 4
     1542552.345      438320.339     1542433.783      438209.681
     1542303.364      438148.423     1542172.945      438014.052
#Sta/Elev= 30
    10.1  669.12    30.4  661.72    40.5  658.17   101.4  637.17   121.6  629.86
   131.8  626.48   141.9  624.21     152  622.75   181.4  618.97     191  617.53
   209.8  614.15   219.8  612.88   229.8  612.92     239  613.49   258.2  615.19
   296.7  618.41   316.1   620.2     326  621.24   335.8  622.42   345.7  624.17
   355.5  626.62   375.3  632.42   385.1  635.42     395  638.58   404.8  641.83
   434.4   651.8     464   662.3   473.8  666.06   483.7  670.13   493.5  674.35
#Mann= 3 , 0 , 0
       0     .08       0   209.8    .045       0   229.8     .08       0
Bank Sta=209.8,229.8
XS Rating Curve= 0 ,0
Exp/Cntr=0.3,0.1

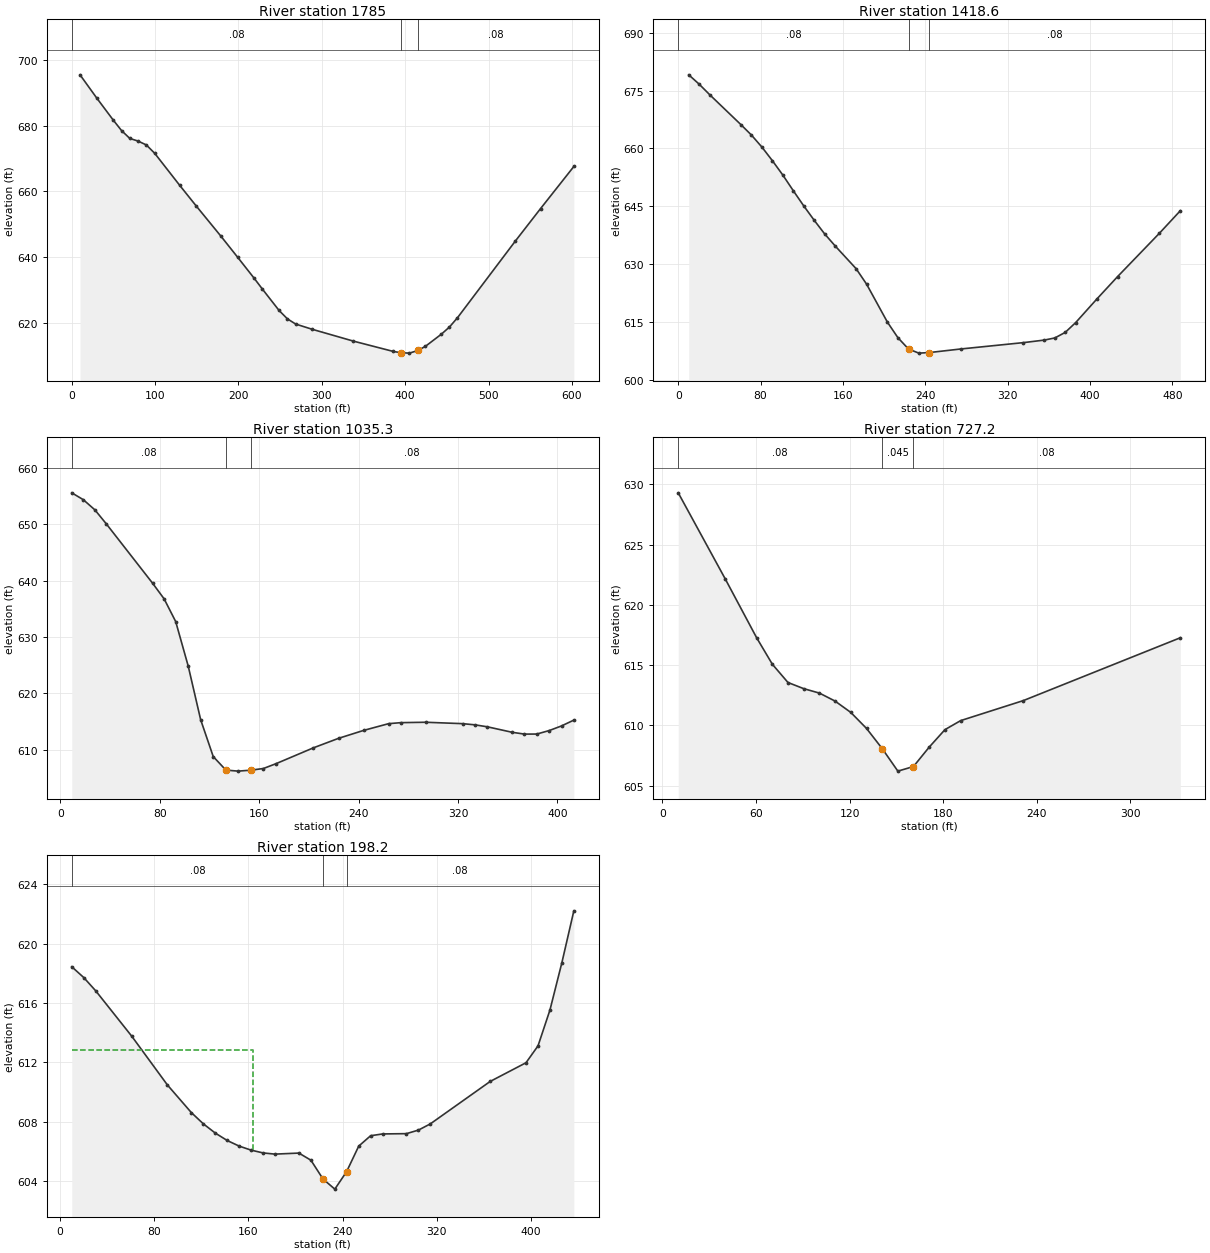
Type RM Length L Ch R = 1 ,1785    ,362.1,366.5,367.9
XS GIS Cut Line= 4
     1542706.477      438338.124     1542520.729      438067.406
     1542415.998      437968.603     1542321.148      437879.682
#Sta/Elev= 30
     9.9  695.47    29.8  688.46    49.7  681.71    59.7  678.51    69.6  676.11
    79.6   675.3    89.5  674.12    99.5  671.58   129.3  661.89   149.2  655.58
   179.1   646.3     199  639.94   218.9  633.52   228.8  630.21   248.7  623.74
   258.7  621.19   268.6  619.61   288.5  618.01   337.9  614.41   385.9  611.26
   395.1  610.88   405.1  610.76   415.1  611.56   424.3  612.84   443.5  616.55
   453.1  618.71   462.7  621.53   532.3  644.93   562.3  654.73   602.3  667.57
#Mann= 3 , 0 , 0
       0     .08       0   395.1    .045       0   415.1     .08       0
Bank Sta=395.1,415.1
XS Rating Curve= 0 ,0
Exp/Cntr=0.3,0.1

Type RM Length L Ch R = 1 ,1418.6  ,370.7,383.3,395.5
XS GIS Cut Line= 2
     1542919.889      438033.813      1542570.13      437693.933
#Sta/Elev= 30
    10.2  679.08    20.3  676.67    30.5  673.95      61  666.15    71.1  663.48
    81.3  660.36    91.4  656.86   101.6  653.12   111.8  649.05   121.9  645.14
   132.1   641.4   142.2  637.89   152.4  634.77   172.7   628.9   182.9  624.89
   203.2  615.02   213.4  610.99   223.7  608.06   233.7     607   243.7  607.14
   274.3  608.07   335.3  609.72   355.6  610.38   365.8  610.93   375.9  612.37
   386.1  614.92   406.4  620.95   426.7   626.8   467.4  638.05   487.7  643.88
#Mann= 3 , 0 , 0
       0     .08       0   223.7    .045       0   243.7     .08       0
Bank Sta=223.7,243.7
XS Rating Curve= 0 ,0
Exp/Cntr=0.3,0.1

Type RM Length L Ch R = 1 ,1035.3  ,314.9,308.1,301.3
XS GIS Cut Line= 4
     1543097.733       437830.28     1543052.284      437749.263
     1543002.883      437585.251     1542886.297      437492.377
#Sta/Elev= 30
     9.3  655.54    18.6  654.32    27.9  652.52    37.2  650.01    74.3  639.53
    83.6  636.75    92.9  632.73     103  624.82     113  615.33   123.1  608.81
   133.3  606.41  143.13  606.23   153.3   606.4   163.4  606.69   173.5  607.54
   203.7  610.36   223.9  612.04     244  613.44   264.2  614.64   274.1  614.82
     294  614.89   323.8  614.64   333.7  614.43   343.7  614.08   363.6  613.11
   373.5  612.79   383.4   612.8   393.4  613.42   403.3  614.24   413.2  615.27
#Mann= 3 , 0 , 0
     9.3     .08       0   133.3    .045       0   153.3     .08       0
Bank Sta=133.3,153.3
XS Rating Curve= 0 ,0
Exp/Cntr=0.3,0.1

Type RM Length L Ch R = 1 ,727.2   ,531,529.1,494
XS GIS Cut Line= 2
     1543392.164      437695.909      1543214.32      437415.311
#Sta/Elev= 18
    10.1  629.29    40.3  622.14    60.4  617.27    70.5  615.07    80.5  613.56
    90.6  613.05   100.7  612.68   110.7  612.02   120.8  611.08   130.9  609.75
     141  608.07     151  606.21     161  606.59   171.1   608.2   181.2  609.65
   191.3   610.4   231.5  612.06   332.2  617.27
#Mann= 3 , 0 , 0
    10.1     .08       0     141    .045       0     161     .08       0
Bank Sta=141,161
XS Rating Curve= 0 ,0
Exp/Cntr=0.3,0.1

Type RM Length L Ch R = 1 ,198.2   ,195.4,198.2,200.4
XS GIS Cut Line= 2
     1543826.894      437660.341     1543579.888      437300.701
#Sta/Elev= 30
    10.1  618.44    20.3  617.71    30.4  616.82    60.9  613.77    91.3  610.47
   111.6  608.61   121.8  607.85   131.9  607.23     142  606.73   152.2  606.35
   162.3  606.08   172.5  605.89   182.6  605.81   202.9  605.88   213.1   605.4
   223.4  604.13   233.4  603.45   243.4  604.63   253.7  606.35   263.8  607.05
     274  607.17   294.2  607.19   304.4  607.43   314.5  607.85   365.3  610.71
   395.7  611.97   405.9  613.11     416  615.52   426.1   618.7   436.3  622.21
#Mann= 3 , 0 , 0
    10.1     .08       0   223.4    .045       0   243.4     .08       0
#XS Ineff= 2 , 0
          163.59  612.82
Permanent Ineff=
       F       F
Bank Sta=223.4,243.4
XS Rating Curve= 0 ,0
Exp/Cntr=0.3,0.1

Chan Stop Cuts=-1
Use User Specified Reach Order=0